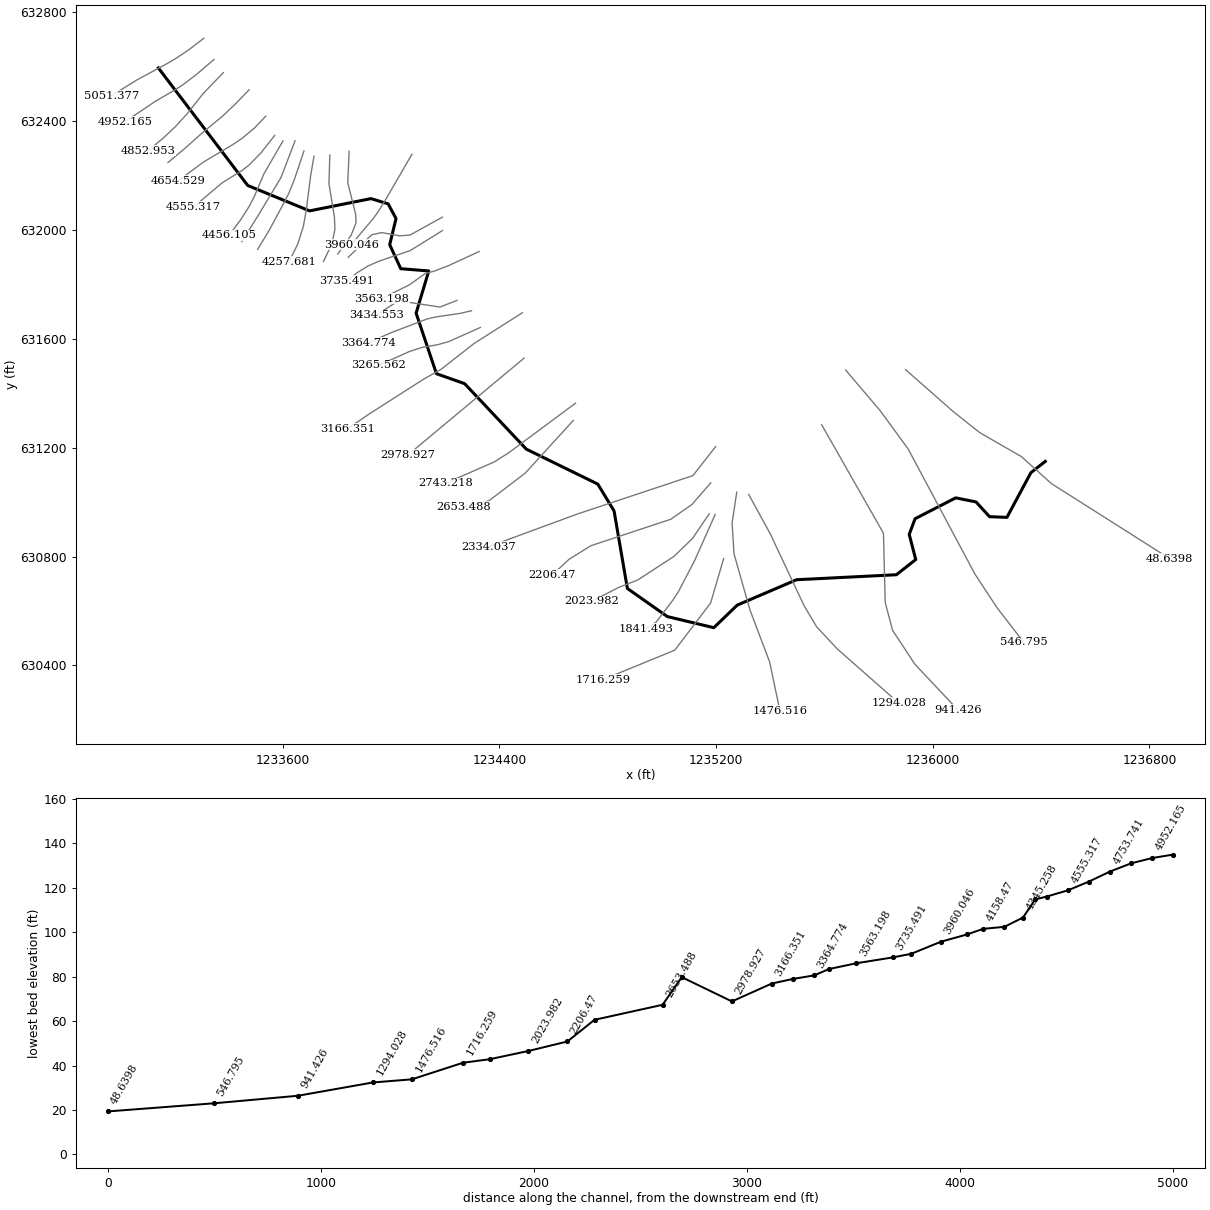
--- 692_ras.prj (project) ---

Proj Title=692
Current Plan=p01
Default Exp/Contr=0.3,0.1
English Units
Geom File=g01
Flow File=f01
Plan File=p01
Y Axis Title=Elevation
X Axis Title(PF)=Main Channel Distance
X Axis Title(XS)=Station
BEGIN DESCRIPTION:
RFD model 692 exported to HEC-RAS
END DESCRIPTION:

--- 692_ras.p01 (plan) ---

Plan Title=Plan 01
Program Version=4.10
Short Identifier=Plan 01
Geom File=g01
Flow File=f01
Subcritical Flow
Calc Critical at every XS
Secant Critical Depth

--- 692_ras.f01 (steady flow) ---

Flow Title=Flow 01
Program Version=5.01
Number of Profiles= 5
Profile Names=10yr,25yr,50yr,100yr,500yr
River Rch & RM=692,33,5051.377
  493.56  610.81  734.29  812.89  999.78
River Rch & RM=692,33,4952.165
   500.7  620.95  746.83  828.53 1021.79
River Rch & RM=692,33,4753.741
  505.95  628.42  756.08  840.08  1038.1
River Rch & RM=692,33,4555.317
  508.83  632.52  761.16  846.44 1047.08
River Rch & RM=692,33,4456.105
  516.21  643.05   774.2  862.77  1070.2
River Rch & RM=692,33,4402.763
  519.01  647.04  779.14  868.98 1079.01
River Rch & RM=692,33,4257.681
  521.78     651  784.06  875.15 1087.76
River Rch & RM=692,33, 4158.47
  523.98  654.15  787.96  880.05 1094.73
River Rch & RM=692,33,4082.887
  630.32  808.45   979.8 1124.64  1448.9
River Rch & RM=692,33,3821.262
  631.56  810.27  982.07 1127.57 1453.22
River Rch & RM=692,33,3735.491
  634.03   813.9   986.6 1133.42 1461.83
River Rch & RM=692,33,3434.553
  654.02  843.39  1023.4 1181.11 1532.34
River Rch & RM=692,33,3364.774
  655.97  846.27    1027 1185.78 1539.28
River Rch & RM=692,33,3166.351
   663.3  857.11 1040.53 1203.39 1565.43
River Rch & RM=692,33,2978.927
  664.44   858.8 1042.65 1206.15 1569.53
River Rch & RM=692,33,2743.218
  682.74  885.96 1076.59 1250.43 1635.55
River Rch & RM=692,33,2653.488
  684.56  888.68 1079.99 1254.86 1642.19
River Rch & RM=692,33,2334.037
  689.99  896.76  1090.1 1268.09 1661.99
River Rch & RM=692,33, 2206.47
  692.51   900.5 1094.78 1274.22 1671.18
River Rch & RM=692,33,2023.982
  698.55  909.52 1106.06    1289 1693.35
River Rch & RM=692,33,1841.493
  699.26  910.57 1107.37 1290.73 1695.94
River Rch & RM=692,33,1716.259
  702.77  915.81 1113.94 1299.34 1708.88
River Rch & RM=692,33,1476.516
  705.91   920.5 1119.81 1307.05 1720.47
River Rch & RM=692,33,1294.028
  713.49  931.84    1134 1325.72 1748.58
River Rch & RM=692,33, 941.426
   737.8  968.33 1179.72 1386.02 1839.78
Boundary for River Rch & Prof#=692,33,1
Up Type= 0
Dn Type= 2
Boundary for River Rch & Prof#=692,33,2
Up Type= 0
Dn Type= 2
Boundary for River Rch & Prof#=692,33,2
Up Type= 0
Dn Type= 2
Boundary for River Rch & Prof#=692,33,2
Up Type= 0
Dn Type= 2
Boundary for River Rch & Prof#=692,33,2
Up Type= 0
Dn Type= 2

--- 692_ras.g01 (geometry) ---

Geom Title=692
Program Version=4.10

River Reach=692,33
Reach XY= 30
1233140.81192595632595.4568063911233470.78623104632163.702720255
1233699.11949429632070.3694079671233925.78609541632115.369388029
1233989.11940944632096.2027251871234018.28606594632042.036073774
1233994.95273671631946.2027695781234035.78605548631857.869461268
1234139.11935803631849.5361274031234092.45270067631694.536174789
  1234167.452672631472.0362386261234271.61930689631435.369579807
1234499.22487429631194.8470401021234763.28581783631066.203008398
1234823.28579724630967.8697025481234872.45244113630682.869785711
1235019.95239463630579.5364787581235191.61900941630538.703152582
1235278.03190845630621.5795418321235497.19851318630714.912841082
1235865.53173834630733.2461582721235937.19838551630789.079472944
1235913.03172866630881.579446211 1235934.6983906630939.079428464
1236084.69834858631015.7460680311236159.69832608631000.746070296
1236209.69830966630946.5794182721236273.86495742630944.079417139
1236362.19826943631108.2460324911236415.42083043631149.746548533

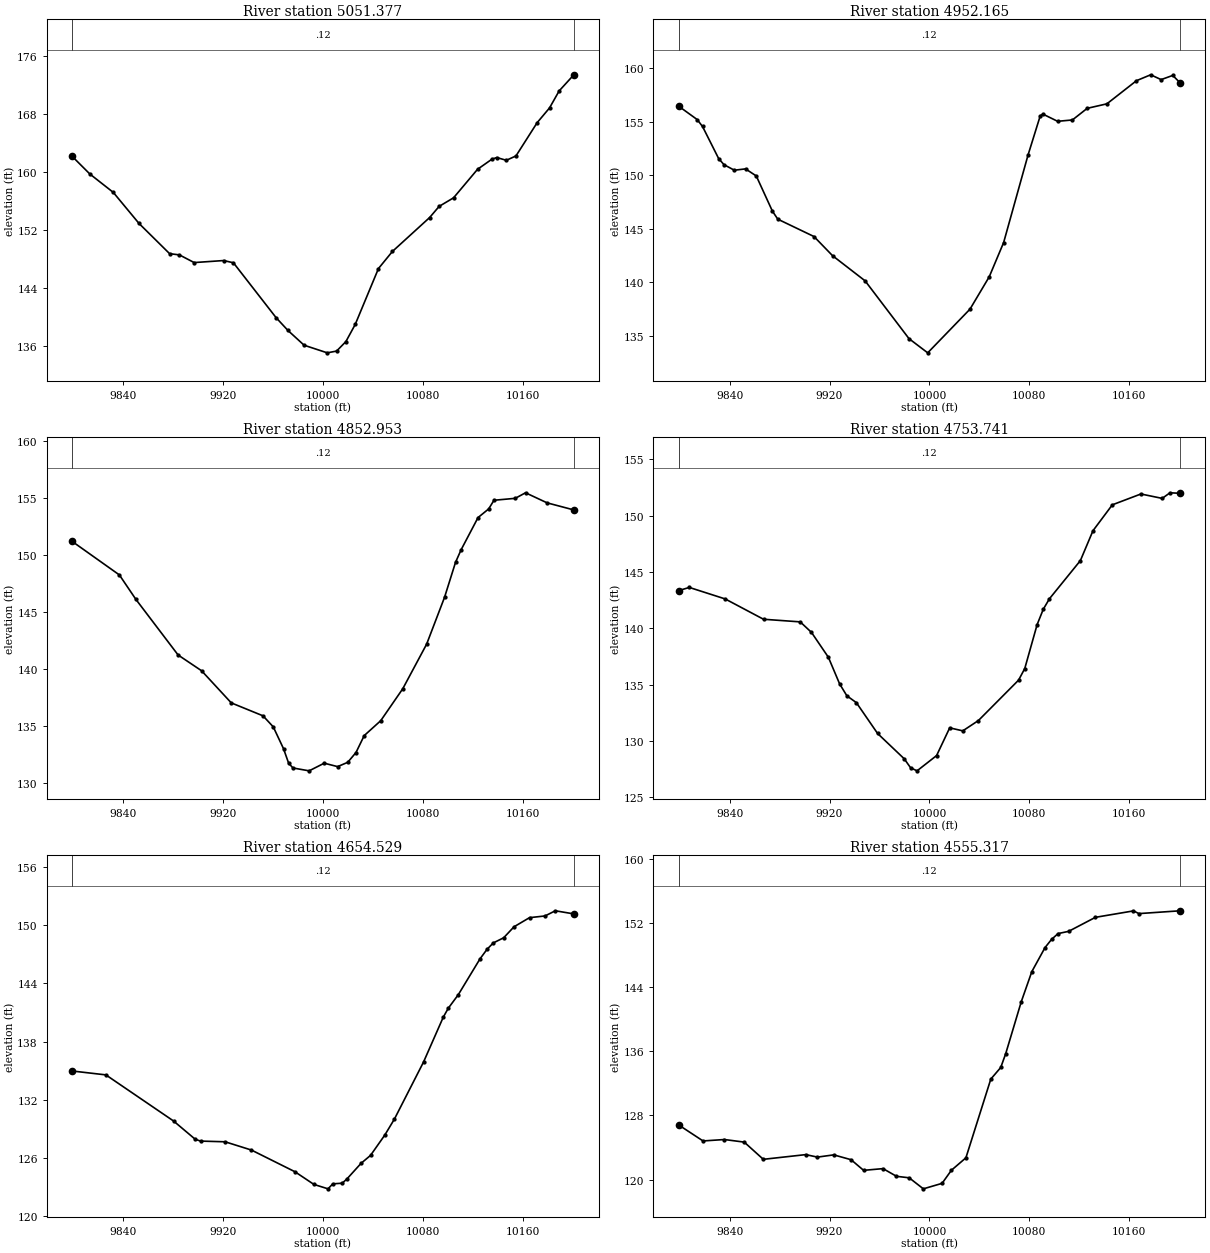
Type RM Length L Ch R = 1 ,5051.377,99.211900,99.211900,99.211900
XS GIS Cut Line= 6
1233308.84458269632704.825578938 1233250.9184163632660.733975238
 1233204.7599853632630.1244893281233166.63143189632607.945378255
1233064.12751905632552.9769649871232967.40145506632493.893378449
#Sta/Elev= 30
9799.028162.1063 9813.24 159.6629832.045157.12179852.661152.83869877.148148.6723
9885.021148.50289896.831147.44389920.451147.72379928.284147.41519962.444139.8505
9971.985138.07759984.905136.046310003.45134.995910010.91135.238210018.36136.5465
10025.82138.904710044.46146.621910055.64148.978610085.47153.658210093.09155.1979
10104.62156.374410123.84160.309910135.38161.705510139.22 161.92710146.91161.5487
 10154.6162.1481 10171.6166.742810181.51 168.775 10189.2171.118810200.98173.3417
#Mann= 3 , 0 , 0
9799.028    0.12       09799.028    0.12       010200.98    0.12       0
#XS Ineff= 2 , 0
       0                               0
Bank Sta=9799.028,10200.98
Exp/Cntr=0.3,0.1

Type RM Length L Ch R = 1 ,4952.165,99.211800,99.211800,99.211800
XS GIS Cut Line= 6
1233346.41952543632626.7515323981233282.15277267632572.095568616
1233232.95329583632534.905806851 1233203.6367154632515.734273352
1233129.33558018 632472.662040471233017.17193906632397.574424569
#Sta/Elev= 30
9799.031156.44429813.936155.18989818.243 154.5429831.164151.5508 9835.47150.9783
9843.731150.46379852.698150.58879861.312149.92879874.232146.64739878.539145.8997
9907.547144.28029922.393142.49659948.505 140.1479983.627134.7626 9998.63133.4374
10032.52137.513710047.91140.526310059.45143.719510079.01151.882910088.77155.5324
10090.86155.6973 10102.7155.023910114.54155.149710126.39156.233410142.18156.6535
10165.87158.811510177.24159.361910185.61158.911910194.93159.301510200.99  158.59
#Mann= 3 , 0 , 0
9799.031    0.12       09799.031    0.12       010200.99    0.12       0
#XS Ineff= 2 , 0
       0                               0
Bank Sta=9799.031,10200.99
Exp/Cntr=0.3,0.1

Type RM Length L Ch R = 1 ,4852.953,99.211900,99.211900,99.211900
XS GIS Cut Line= 6
1233381.18009768632578.6633048951233306.86616488 632502.30858062
1233251.75858117 632432.592349931233204.80467548632380.985025762
1233161.09363383632339.8325214591233102.04305592632290.972593584
#Sta/Elev= 30
9799.033151.21529836.927148.26269850.168146.11259883.966141.22599902.782139.8391
9926.556137.01639951.969 135.8799960.181134.90889968.393132.99089972.499131.7147
9975.971131.29479988.923131.0433   10001131.715810011.72131.4138 10019.8131.7908
10026.45132.655210033.03134.141210046.26 135.451 10063.9138.257410083.02142.1774
10097.38 146.29910106.16149.367610110.67150.481510124.19153.304910132.71154.0655
10136.97154.8272   10154 154.99610162.25155.484210179.55154.597510200.95153.9756
#Mann= 3 , 0 , 0
9799.033    0.12       09799.033    0.12       010200.95    0.12       0
#XS Ineff= 2 , 0
       0                               0
Bank Sta=9799.033,10200.95
Exp/Cntr=0.3,0.1

Type RM Length L Ch R = 1 ,4753.741,99.211900,99.211900,99.211900
XS GIS Cut Line= 6
1233475.91406671632515.4097446331233425.18945269 632463.14659905
1233375.81230414632416.6349061391233306.88331969632360.367744544
1233236.11236784632297.7448271931233176.25845904632248.019367008
#Sta/Elev= 30
 9799.03143.34879807.669143.63429836.389142.61299867.105140.80829896.515140.5757
9905.529139.64129919.051137.43499928.065135.06869933.872134.01099941.481 133.403
9958.501 130.6639979.796128.41879984.948127.6152  9990.1127.346810005.74128.7023
10016.24131.163610026.75130.898310039.24131.812810071.42135.402510076.37136.4302
10086.27140.328910091.22141.699910096.17 142.63210120.92146.015910131.02148.6703
10146.51150.969310169.41151.932210186.47151.541910192.72152.039910200.99151.9927
#Mann= 3 , 0 , 0
 9799.03    0.12       0 9799.03    0.12       010200.99    0.12       0
#XS Ineff= 2 , 0
       0                               0
Bank Sta=9799.03,10200.99
Exp/Cntr=0.3,0.1

Type RM Length L Ch R = 1 ,4654.529,99.211900,99.211900,99.211900
XS GIS Cut Line= 6
1233537.48891409632418.5708461461233496.00517793632375.129153178
1233449.16424573  632336.22088841233414.04321633632312.968434155
1233306.64301377632249.342760821 1233215.0284229632181.587877677
#Sta/Elev= 30
9799.079134.96999826.152134.56799880.362129.81519897.764 127.9289902.029127.7444
 9921.66127.67269942.771126.8189  9977.6124.58489992.765123.279810004.11122.8235
10007.89 123.33810015.45123.404210019.23123.842510030.56125.452710038.12 126.269
10049.56128.364410057.31130.024710080.57135.889110096.39140.5149 10100.4141.4357
10108.42142.830210125.76146.514510131.46147.5126 10136.5 148.17110144.78148.6988
10153.05149.829310165.46150.771410177.87150.946510186.15151.480810200.99 151.159
#Mann= 3 , 0 , 0
9799.079    0.12       09799.079    0.12       010200.99    0.12       0
#XS Ineff= 2 , 0
       0                               0
Bank Sta=9799.079,10200.99
Exp/Cntr=0.3,0.1

Type RM Length L Ch R = 1 ,4555.317,99.211900,99.211900,99.211900
XS GIS Cut Line= 6
1233570.50007572632347.6853350611233518.03509594632281.653737343
1233474.60472985632237.9049495281233450.00124583632218.976913386
1233375.72107134632173.0533144641233270.72198723632084.467001896
#Sta/Elev= 30
9799.085126.82829818.704124.82189835.826124.99889851.697124.67679866.986122.5304
9901.003123.11729910.316122.80659923.395123.08529937.264122.48269947.296121.1567
9962.883121.37039973.644120.41349983.816120.2255 9995.15  118.8510010.15119.5348
10017.66121.171910029.24 122.71810049.18132.533510057.15133.985110061.14135.7166
10073.62142.203810082.04145.937210092.61148.935110097.85149.955810103.06150.6817
10111.48150.956410132.97 152.70710163.46153.509210167.82153.171910200.97153.5234
#Mann= 3 , 0 , 0
9799.085    0.12       09799.085    0.12       010200.97    0.12       0
#XS Ineff= 2 , 0
       0                               0
Bank Sta=9799.085,10200.97
Exp/Cntr=0.3,0.1

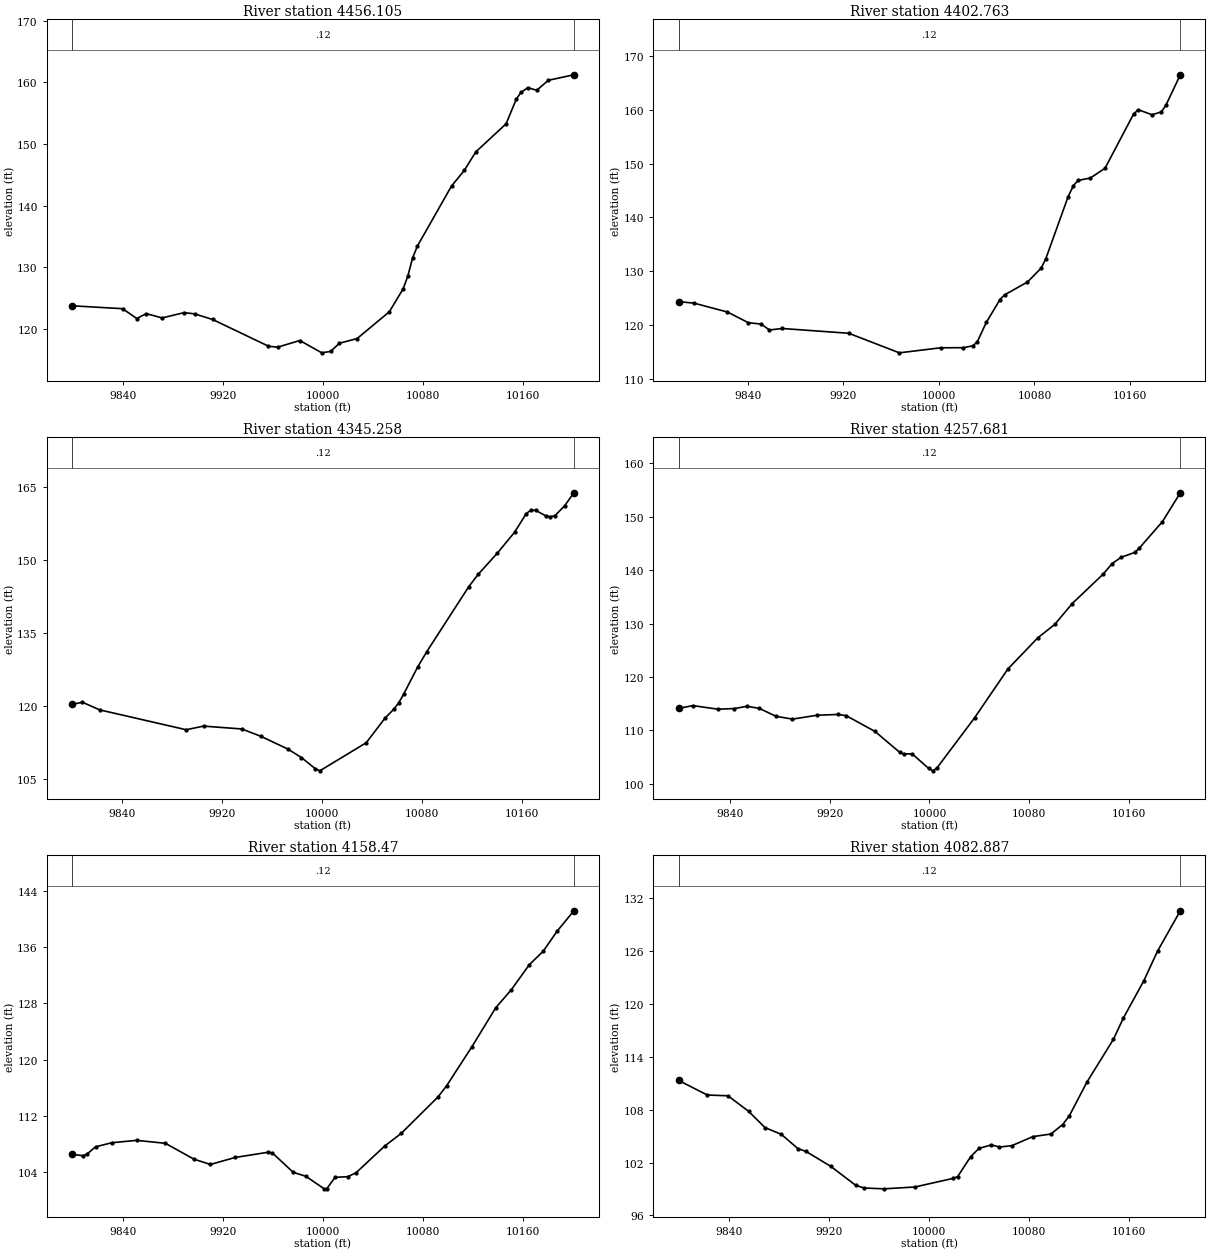
Type RM Length L Ch R = 1 ,4456.105,53.342600,53.342600,53.342600
XS GIS Cut Line= 6
1233600.94456819632327.6481839061233530.25618506632206.054173707
1233495.55853804632124.1839519081233476.57914242632087.628724398
1233444.57239015632037.7115004621233401.59574622631980.161018835
#Sta/Elev= 30
9799.028123.71719839.481123.24639850.866121.65019858.456122.44919871.096121.7419
9888.815122.60689897.208122.40359911.585121.49239956.353117.15119963.607116.9893
 9981.44118.07479999.048116.072510006.11116.3112 10013.2117.635310027.37118.3995
 10053.2122.754810064.29126.502110067.98128.561310071.78131.496610075.68133.4416
10102.96143.174510113.18145.713110122.45148.732610146.68153.285310154.87157.3089
10158.61158.396110164.09159.153810171.24158.732610180.54160.355710200.95161.2497
#Mann= 3 , 0 , 0
9799.028    0.12       09799.028    0.12       010200.95    0.12       0
#XS Ineff= 2 , 0
       0                               0
Bank Sta=9799.028,10200.95
Exp/Cntr=0.3,0.1

Type RM Length L Ch R = 1 ,4402.763,57.504100,57.504100,57.504100
XS GIS Cut Line= 4
1233645.55078727632327.6693076041233593.61624208632192.964080974
1233509.22260609632053.3899906871233449.17328817631957.635672957
#Sta/Elev= 30
9781.774124.33599794.665124.06129822.795122.39929840.376120.40219850.925120.1716
9857.957119.05859868.506119.34019924.379 118.4489966.814114.805410001.32115.7422
10020.49115.768810028.16116.100310031.99116.802710039.66120.464210051.16 124.729
   10055125.598810074.17 127.98810085.67130.5844 10089.5   132.310108.29143.9005
10112.74145.953210116.61146.898210126.81147.339710139.16149.160310163.08159.2458
10166.96  160.0710178.57159.116510186.32159.649910190.19 160.89810202.27166.5631
#Mann= 3 , 0 , 0
9781.774    0.12       09781.774    0.12       010202.27    0.12       0
#XS Ineff= 2 , 0
       0                               0
Bank Sta=9781.774,10202.27
Exp/Cntr=0.3,0.1

Type RM Length L Ch R = 1 ,4345.258,87.577100,87.577100,87.577100
XS GIS Cut Line= 6
1233678.47481902632290.7270967861233642.23375571632183.453191803
1233621.98102735632134.155919151 1233606.0342059632102.496109167
1233549.83311878631998.6676415711233507.21482847631928.710320247
#Sta/Elev= 30
9799.703120.28769808.035120.72029821.887119.15789891.148115.0744    9905115.8214
9935.597115.23519950.917113.72899972.414111.12759983.439109.36589994.463107.0861
9998.138106.629410035.38 112.412 10050.3117.435910057.76119.391510061.49120.6709
10065.22122.342610076.41 127.90810083.88 131.14210117.45144.473710125.07147.0295
10140.43151.392710154.18 155.67210163.48159.481510167.33160.240810171.17160.1526
10179.41159.003810182.69158.844410186.53159.080210194.22  161.0910201.66163.7791
#Mann= 3 , 0 , 0
9799.703    0.12       09799.703    0.12       010201.66    0.12       0
#XS Ineff= 2 , 0
       0                               0
Bank Sta=9799.703,10201.66
Exp/Cntr=0.3,0.1

Type RM Length L Ch R = 1 ,4257.681,99.211900,99.211900,99.211900
XS GIS Cut Line= 6
  1233715.441744632271.1673072221233702.99516509632199.279938787
1233687.03220912 632074.163133891233676.13927505632013.490860881
1233655.89092378631949.5597656421233623.22409544 631883.10919237
#Sta/Elev= 30
9799.017114.11789810.485114.65349830.463113.98339843.782114.09819853.771 114.522
9863.759 114.1299877.044112.65069890.274  112.129910.118112.85239926.655112.9913
 9933.27 112.7749956.422109.80529976.267105.88099979.574105.60599986.189105.6102
9999.424102.876910002.75102.435210006.09 103.00210036.09112.345110062.83121.5069
10086.67127.315610100.41129.862110114.36133.762910139.16139.270610146.36141.2511
10153.57142.423210164.37143.325110167.97144.108610186.62149.101510200.95154.5037
#Mann= 3 , 0 , 0
9799.017    0.12       09799.017    0.12       010200.95    0.12       0
#XS Ineff= 2 , 0
       0                               0
Bank Sta=9799.017,10200.95
Exp/Cntr=0.3,0.1

Type RM Length L Ch R = 1 , 4158.47,75.583000,75.583000,75.583000
XS GIS Cut Line= 6
1233773.92331387632275.299146902 1233770.5765309632170.400821164
1233790.80739025632047.6497739641233792.66546145632003.640253669
1233781.98131082631949.4548512731233750.22021324631884.103154522
#Sta/Elev= 30
9799.074106.45239807.976106.27719811.268106.53429817.852107.53979831.021108.1269
 9850.77108.46059873.739108.04339896.707105.77369909.871105.02399929.692106.0198
 9956.12106.76499959.436106.67429976.185103.89529986.234103.3374   10001101.5414
10002.99101.544910009.68103.1819 10019.7103.276610026.38103.820310049.48107.6618
 10062.6109.446810092.26114.688210098.93116.233810119.26121.828110138.26127.3656
10150.92129.985210165.21133.533210176.24135.437710187.56138.334210200.89141.2318
#Mann= 3 , 0 , 0
9799.074    0.12       09799.074    0.12       010200.89    0.12       0
#XS Ineff= 2 , 0
       09941.908                       0
Bank Sta=9799.074,10200.89
Exp/Cntr=0.3,0.1

Type RM Length L Ch R = 1 ,4082.887,122.840800,122.840800,122.840800
XS GIS Cut Line= 6
1233845.15203437632289.357934882 1233840.0872254632173.530563933
1233869.16014118632058.4727134881233870.78765025632027.098954529
1233852.61005642631980.9048404281233803.13054677631911.632502749
#Sta/Elev= 30
9799.427111.32819822.488109.66729838.986109.58169855.484107.82229868.635105.9728
9881.763105.2006 9894.89103.59759901.454103.26549921.226101.57959941.20699.42489
9947.86699.118149963.76599.020379988.62799.23032 10019.5100.215910022.92100.4208
 10033.2102.655710039.87 103.60610049.81104.007410056.37103.768110066.22103.9182
10083.13104.949210097.49 105.23810106.88106.3102 10112.2107.287510126.23111.1019
10147.53115.9857 10155.5118.394410171.88122.627910182.86125.991810201.13130.5781
#Mann= 3 , 0 , 0
9799.427    0.12       09799.427    0.12       010201.13    0.12       0
#XS Ineff= 2 , 0
       09949.371                       0
Bank Sta=9799.427,10201.13
Exp/Cntr=0.3,0.1

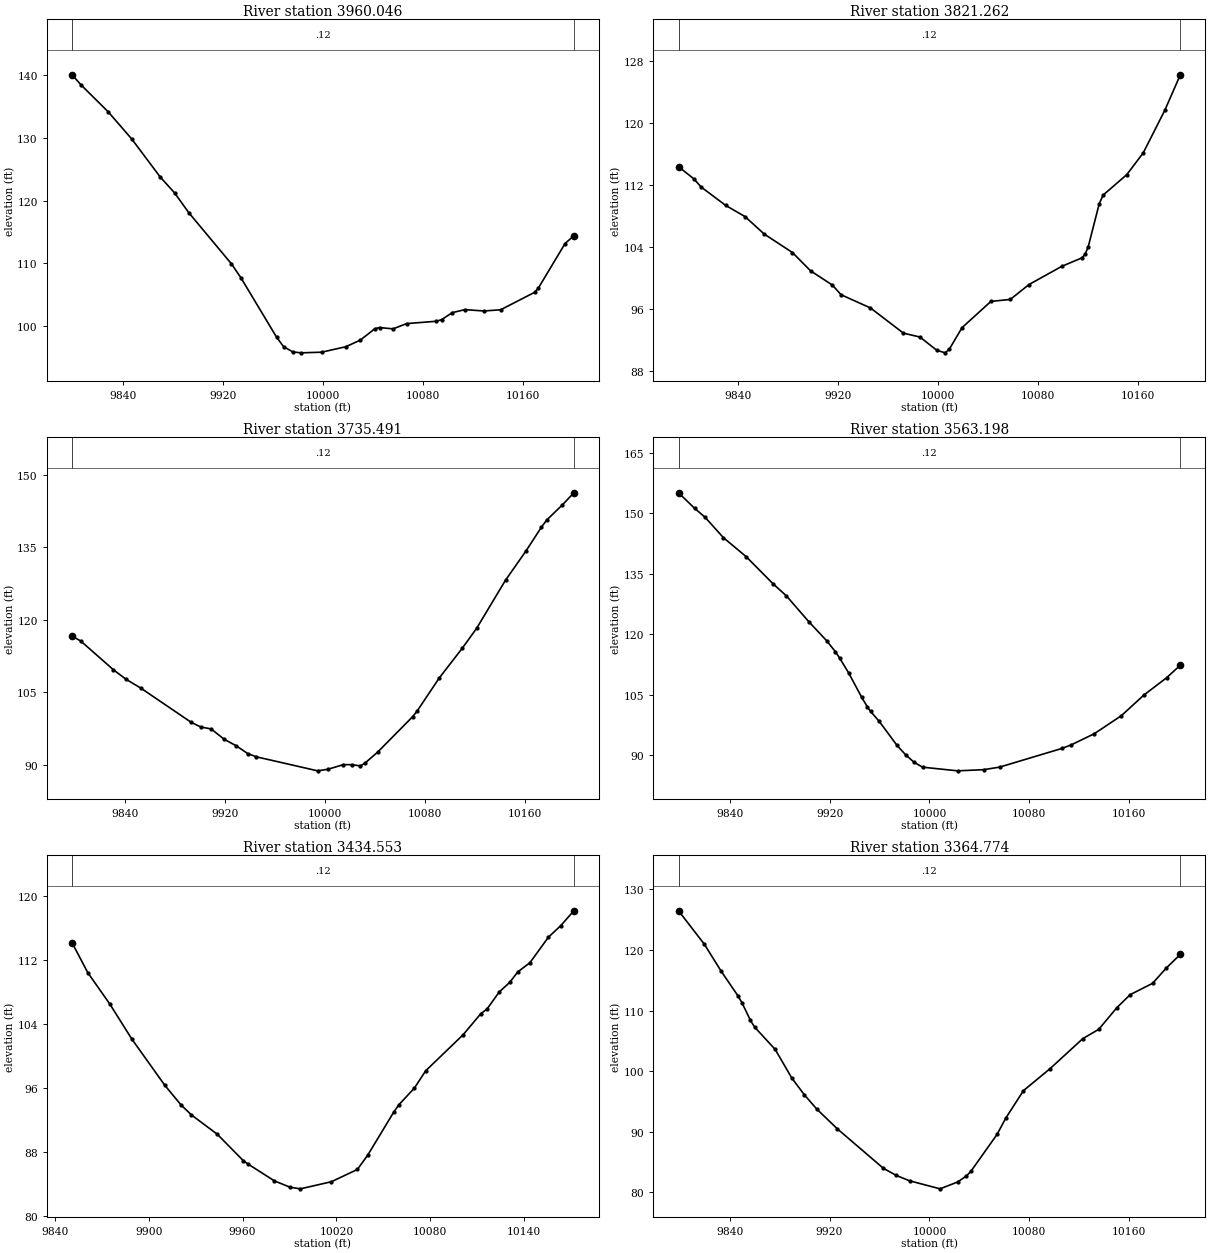
Type RM Length L Ch R = 1 ,3960.046,138.783900,138.783900,138.783900
XS GIS Cut Line= 6
 1234076.9206459632278.305386169 1233982.6773358632116.393410262
1233976.09860452632105.5827181931233948.93706116632062.378314695
1233931.05907287 632038.377323791233852.74127786631946.120278894
#Sta/Elev= 30
9799.002140.08769806.293138.45019827.929134.1826 9846.91129.82029869.687123.7677
9881.075121.26449892.463118.10399926.629109.94489934.221107.72759962.81898.24728
9968.38696.734559975.86195.893129982.38395.74342  9998.995.8446610018.28 96.7178
 10029.9 97.771410041.5399.58561 10045.499.7739610056.1299.5680710067.11100.4085
10090.68100.777810094.98101.029910103.58102.154510113.72102.634610128.93102.4182
10142.32102.610510169.49105.388810172.44106.042410193.96113.179310200.98114.4209
#Mann= 3 , 0 , 0
9799.002    0.12       09799.002    0.12       010200.98    0.12       0
#XS Ineff= 2 , 0
       0                               0
Bank Sta=9799.002,10200.98
Exp/Cntr=0.3,0.1

Type RM Length L Ch R = 1 ,3821.262,85.771200,85.771200,85.771200
XS GIS Cut Line= 6
1234189.38916683632047.1814733211234070.18457598 631981.67222654
1234032.36579618631978.4172725331233966.06951184631990.554794427
  1233928.738436631982.8450050571233841.83517662631899.805759986
#Sta/Elev= 30
9792.444114.34319804.805112.75769810.492111.72249830.193109.34219845.638107.9024
 9860.98105.65239883.607103.25969898.149100.89739915.64399.053929922.55597.81035
9946.08696.106689972.446 92.85579985.77692.347399999.20290.6350810005.9690.31201
10009.3490.8193910019.4293.56843 10042.596.9513410058.0497.2074110073.0399.13332
10099.28101.479910115.45 102.57810117.99103.063710120.37103.988910129.27109.5882
10132.37  110.6810151.26113.312210164.45116.124510181.63121.594810194.13126.2045
#Mann= 3 , 0 , 0
9792.444    0.12       09792.444    0.12       010194.13    0.12       0
#XS Ineff= 2 , 0
       0                               0
Bank Sta=9792.444,10194.13
Exp/Cntr=0.3,0.1

Type RM Length L Ch R = 1 ,3735.491,172.292500,172.292500,172.292500
XS GIS Cut Line= 6
 1234189.6006341631997.8898128021234069.96681522631924.091993306
1233956.80318512631886.016855162 1233915.6107321631868.259666158
1233874.92244438631843.1733065211233836.31505998  631812.8776613
#Sta/Elev= 30
9797.227116.60239804.153115.59239830.326109.63149840.315107.68389852.369105.8132
 9892.7798.720249900.28497.780999908.61297.37306 9919.0795.22576 9928.8193.86568
9937.86192.278689944.90691.592769993.87688.6943710002.1689.0194110014.4589.98167
10021.3289.9693810028.1889.7171810031.6290.2598410041.9192.5613210069.8799.88675
10073.44101.0343 10091.3107.939710109.72114.096210121.28118.2458 10144.4128.2111
10160.63134.198210173.14 139.18210177.31140.640710189.82143.761410199.07146.2892
#Mann= 3 , 0 , 0
9797.227    0.12       09797.227    0.12       010199.07    0.12       0
#XS Ineff= 2 , 0
       0                               0
Bank Sta=9797.227,10199.07
Exp/Cntr=0.3,0.1

Type RM Length L Ch R = 1 ,3563.198,128.644600,128.644600,128.644600
XS GIS Cut Line= 6
1234325.27232838631921.0075424841234212.10583257631869.093289124
 1234161.0557066631849.5966250041234125.45472849631839.831485497
1234067.34925789631798.2482063641233964.84083117631748.138305514
#Sta/Elev= 30
9799.041155.12949811.834151.29549820.288 149.0459834.902143.99989853.169139.2704
9874.678132.53529885.404129.52169903.281123.13019917.583118.39969924.714115.6257
9928.226 113.984 9935.25110.38739945.785104.27569950.175 102.0049952.809100.8266
9959.83398.312169973.881 92.42259980.81990.055919987.61888.188299994.41786.96168
10022.5186.0488610043.3986.3370410056.1586.9739410106.0691.6149810113.4792.49842
10131.9595.2619910153.6799.7519410171.77104.892210189.87109.166710200.89112.2912
#Mann= 3 , 0 , 0
9799.041    0.12       09799.041    0.12       010200.89    0.12       0
#XS Ineff= 2 , 0
       0                               0
Bank Sta=9799.041,10200.89
Exp/Cntr=0.3,0.1

Type RM Length L Ch R = 1 ,3434.553,69.779200,69.779200,69.779200
XS GIS Cut Line= 4
1234243.43118489631741.2930628211234180.13595787631716.948744774
1234026.94510373631740.1597648711233944.80754989631686.112608552
#Sta/Elev= 30
9850.906114.15329860.996110.41039875.056106.50459889.117102.13959910.20896.37146
9920.63993.907979927.276 92.66499943.86790.245889960.45886.955959963.77786.49842
9980.36884.430459990.32383.64251 9996.9683.4371810016.8784.3253610033.4685.85834
 10040.187.6454310056.6993.0007110060.0193.9296910069.9696.02003 10077.298.17795
10101.07102.659510112.48105.306310116.41105.883110124.27108.017110130.92109.1974
10136.05110.5062 10143.9111.669910155.69114.845310163.54116.276310171.98118.1451
#Mann= 3 , 0 , 0
9850.906    0.12       09850.906    0.12       010171.98    0.12       0
#XS Ineff= 2 , 0
       0                               0
Bank Sta=9850.906,10171.98
Exp/Cntr=0.3,0.1

Type RM Length L Ch R = 1 ,3364.774,99.211800,99.211800,99.211800
XS GIS Cut Line= 6
  1234296.871975631703.3642649291234255.44291096631693.787499957
1234164.22513778 631680.459272681234133.28870101631673.309466441
 1233996.5001771631621.3088670681233915.21311803 631584.86739983
#Sta/Elev= 30
9799.063  126.479819.803120.93069833.273116.47289846.663112.42639849.979111.2469
 9856.61108.39379859.926107.28699876.504103.57449889.76798.860099899.71496.12131
9909.66193.761729926.239 90.47139963.16283.951849973.56182.77199 9984.0581.89764
 10008.5 80.566710022.5781.69868 10029.682.6823710033.1283.4306910054.2289.56605
10061.2692.2806910075.3296.7763510096.42  100.3710122.84105.359610135.63 106.899
10150.01110.4495 10160.8112.624810178.77114.494910189.56116.987310200.96119.2709
#Mann= 3 , 0 , 0
9799.063    0.12       09799.063    0.12       010200.96    0.12       0
#XS Ineff= 2 , 0
       0                               0
Bank Sta=9799.063,10200.96
Exp/Cntr=0.3,0.1

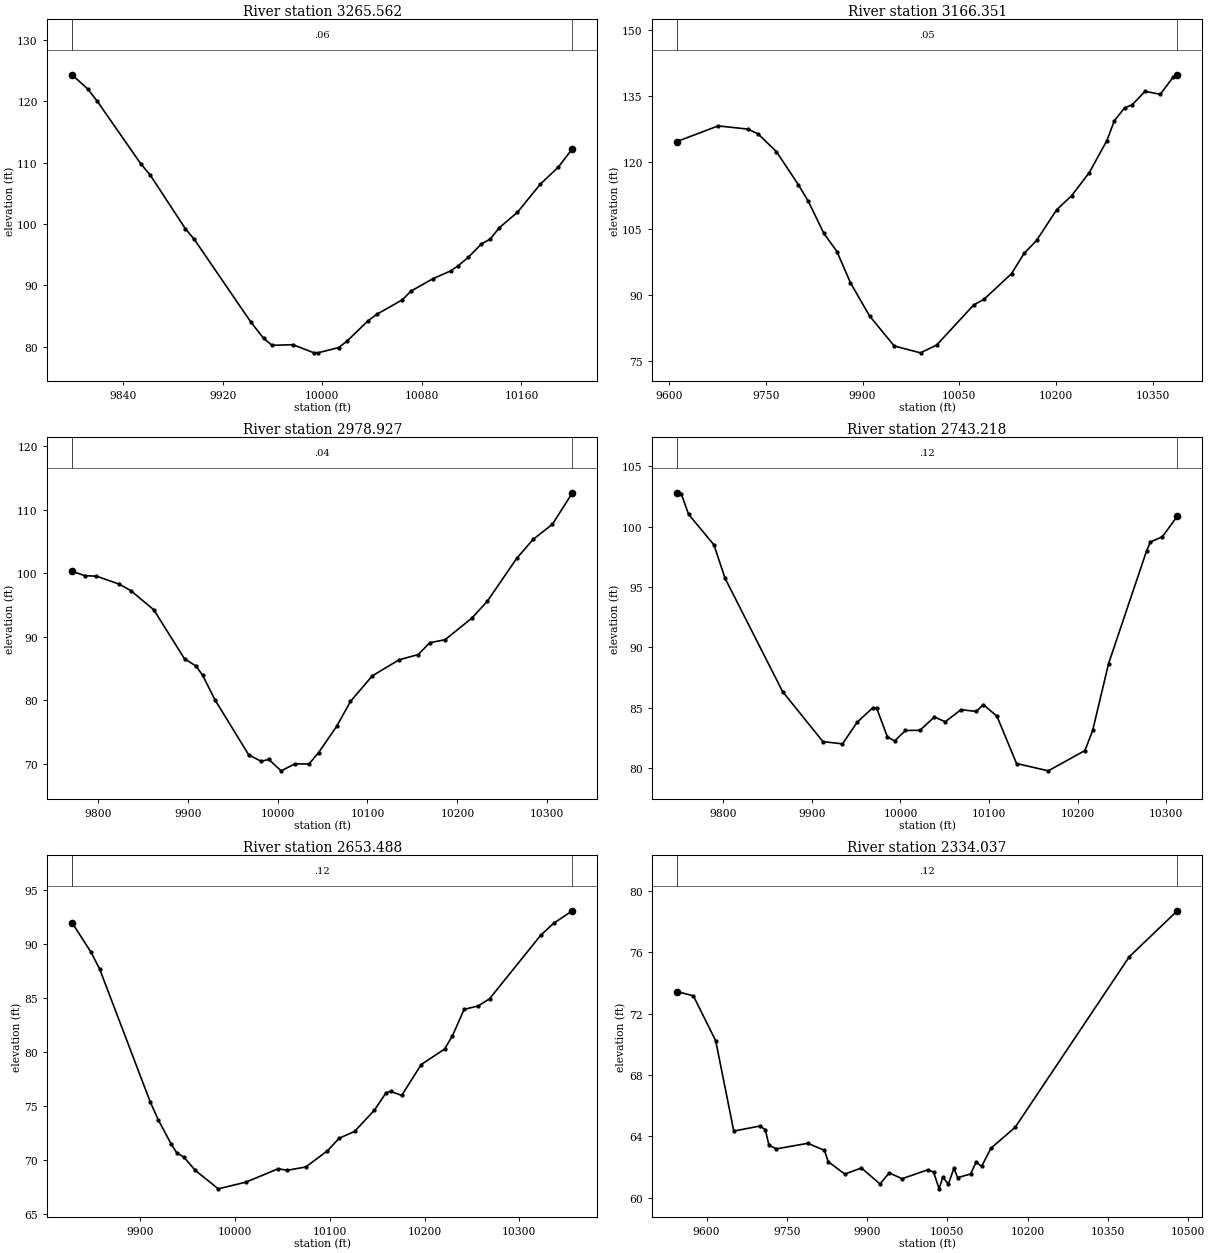
Type RM Length L Ch R = 1 ,3265.562,99.211900,99.211900,99.211900
XS GIS Cut Line= 6
1234329.88648236631641.9547817771234212.78049886631589.980572498
1234173.00072306631578.7889759871234113.80957009631568.394033537
1234067.94774758631553.6838497161233954.77671622631502.852834848
#Sta/Elev= 30
9799.057124.29959811.725121.98559819.356119.9904 9854.37109.76179861.638108.0307
9890.20499.180749897.27797.475939942.67184.004019952.89681.359619959.71280.20629
9976.55880.305189993.19479.000269996.521 78.981210013.1879.8373410019.8680.87519
 10036.884.2007210043.6985.2405710064.3687.6213110071.2689.0361510088.8491.05296
10103.0592.3235710109.0193.1403510117.2594.5344410127.9196.7311210135.01 97.5319
10142.2299.36941 10156.8101.880410175.02106.4336 10189.6109.239810200.94112.2466
#Mann= 3 , 0 , 0
9799.057    0.06       09799.057    0.06       010200.94    0.06       0
#XS Ineff= 2 , 0
       0                               0
Bank Sta=9799.057,10200.94
Exp/Cntr=0.3,0.1

Type RM Length L Ch R = 1 ,3166.351,187.423200,187.423200,187.423200
XS GIS Cut Line= 6
1234484.84971243 631695.976230511234306.36055639631583.007805747
1234184.32444202631487.9042620621234120.23423326631451.941985831
1233922.67196248631326.1912729121233838.11284248631269.400911342
#Sta/Elev= 30
9612.228124.71169676.118128.25029722.711127.51499738.242126.39589766.367122.4354
9800.366114.95899815.897111.19199839.962 103.9359860.32399.820839880.98192.82459
9910.75585.271489949.09978.454999989.75976.9165810014.7778.6728310072.47 87.7838
10088.0389.0075410130.81 94.828110150.2599.39147 10169.7102.346610200.81109.2732
10224.14112.487310251.37117.690710278.59124.923610290.33129.438610306.07132.3248
10317.84133.022910337.75136.061510361.47135.400710381.23139.258610387.83139.8117
#Mann= 3 , 0 , 0
9612.228    0.05       09612.228    0.05       010387.83    0.05       0
#XS Ineff= 2 , 0
       0                               0
Bank Sta=9612.228,10387.83
Exp/Cntr=0.3,0.1

Type RM Length L Ch R = 1 ,2978.927,235.709000,235.709000,235.709000
XS GIS Cut Line= 2
1234491.11010161 631529.175674931234062.65010357631173.748631105
#Sta/Elev= 30
9771.287 100.3039785.62499.588739798.44499.522939823.98898.260299836.77797.23344
9862.35394.211259896.45586.499799909.24385.367179916.63383.902789930.557  79.989
 9968.0271.34153 9981.7170.373589990.23570.6450310003.9968.8572910019.41 69.9639
10034.8269.9236110045.6571.7319210065.6575.8508610081.0779.7886110105.3383.81448
10135.1786.3460210156.4887.1716910169.2789.0353110186.3289.5085210216.16 92.9173
10233.2195.5448210266.06102.329910284.36 105.32410305.68107.680910327.98112.6525
#Mann= 3 , 0 , 0
9771.287    0.04       09771.287    0.04       010327.98    0.04       0
#XS Ineff= 2 , 0
       0                               0
Bank Sta=9771.287,10327.98
Exp/Cntr=0.3,0.1

Type RM Length L Ch R = 1 ,2743.218,89.730200,89.730200,89.730200
XS GIS Cut Line= 4
1234680.99578255631363.6343120491234432.68373823 631180.24044925
1234380.74919298 631147.781358481234202.22419381631069.879540667
#Sta/Elev= 30
9747.726102.79669752.786102.66669760.943101.00749789.49398.487129801.99995.72753
9866.98886.344249912.44782.209899934.53782.017159951.10483.808419968.95385.01914
9973.03284.988579985.26882.596819993.42582.2596610005.6683.1278610021.9883.14018
10038.2984.2418810050.5383.8515410068.3684.8477110085.6584.7032810093.3985.27265
10108.8684.30942   10131 80.393210166.7979.7871110208.1981.4671510216.91  83.135
10234.8188.6502610277.7697.9914310282.0298.7206310295.6699.1687810312.45100.8557
#Mann= 3 , 0 , 0
9747.726    0.12       09747.726    0.12       010312.45    0.12       0
#XS Ineff= 2 , 0
       0                10118.84       0
Bank Sta=9747.726,10312.45
Exp/Cntr=0.3,0.1

Type RM Length L Ch R = 1 ,2653.488,319.451200,319.451200,319.451200
XS GIS Cut Line= 4
1234672.88100985631300.3390850571234495.97896519631107.207495034
1234361.27373853631004.9613591581234267.14237535630982.239995599
#Sta/Elev= 30
9828.10192.01016 9848.2889.245379857.17887.723869910.56775.407569919.25973.70405
9932.81371.476419938.688 70.6644 9946.1670.274079958.11769.050129982.40467.33683
10011.5567.9557410045.5569.1968410055.2669.0582110074.6969.3613110097.6170.86677
10109.9172.0255410126.1972.6577710147.0474.61708 10159.4 76.237910164.1876.37071
10175.8775.9941710196.4778.8515710221.1880.29544 10229.381.4945910241.7883.97005
10256.4384.2787910268.5384.9454710322.5390.8335810336.0891.9393410355.9693.10285
#Mann= 3 , 0 , 0
9828.101    0.12       09828.101    0.12       010355.96    0.12       0
#XS Ineff= 2 , 0
       0                               0
Bank Sta=9828.101,10355.96
Exp/Cntr=0.3,0.1

Type RM Length L Ch R = 1 ,2334.037,127.567000,127.567000,127.567000
XS GIS Cut Line= 4
1235198.71828017631204.5847673271235114.32464418631097.469767809
1234687.48760065630956.2727230041234359.65078402630836.174087197
#Sta/Elev= 30
9544.61373.43106 9575.3173.152119617.07870.222479650.86564.341519699.362 64.6687
9709.72964.438039716.64163.417489730.463 63.1847 9789.2163.546559820.31163.08322
9827.22262.354219858.32461.539749889.42561.939739923.982 60.8963 9941.2661.61409
 9965.4561.2423410013.8361.82318 10024.2 61.669910034.5660.5803210041.4761.34366
10051.8460.8832310062.2161.9240510069.1261.3089610093.31 61.548810103.6862.31336
10114.0462.0450310131.3363.2217210176.7564.5919510389.8975.6949610479.7178.69084
#Mann= 3 , 0 , 0
9544.613    0.12       09544.613    0.12       010479.71    0.12       0
#XS Ineff= 2 , 0
       09950.476        10166.06       0
Bank Sta=9544.613,10479.71
Exp/Cntr=0.3,0.1

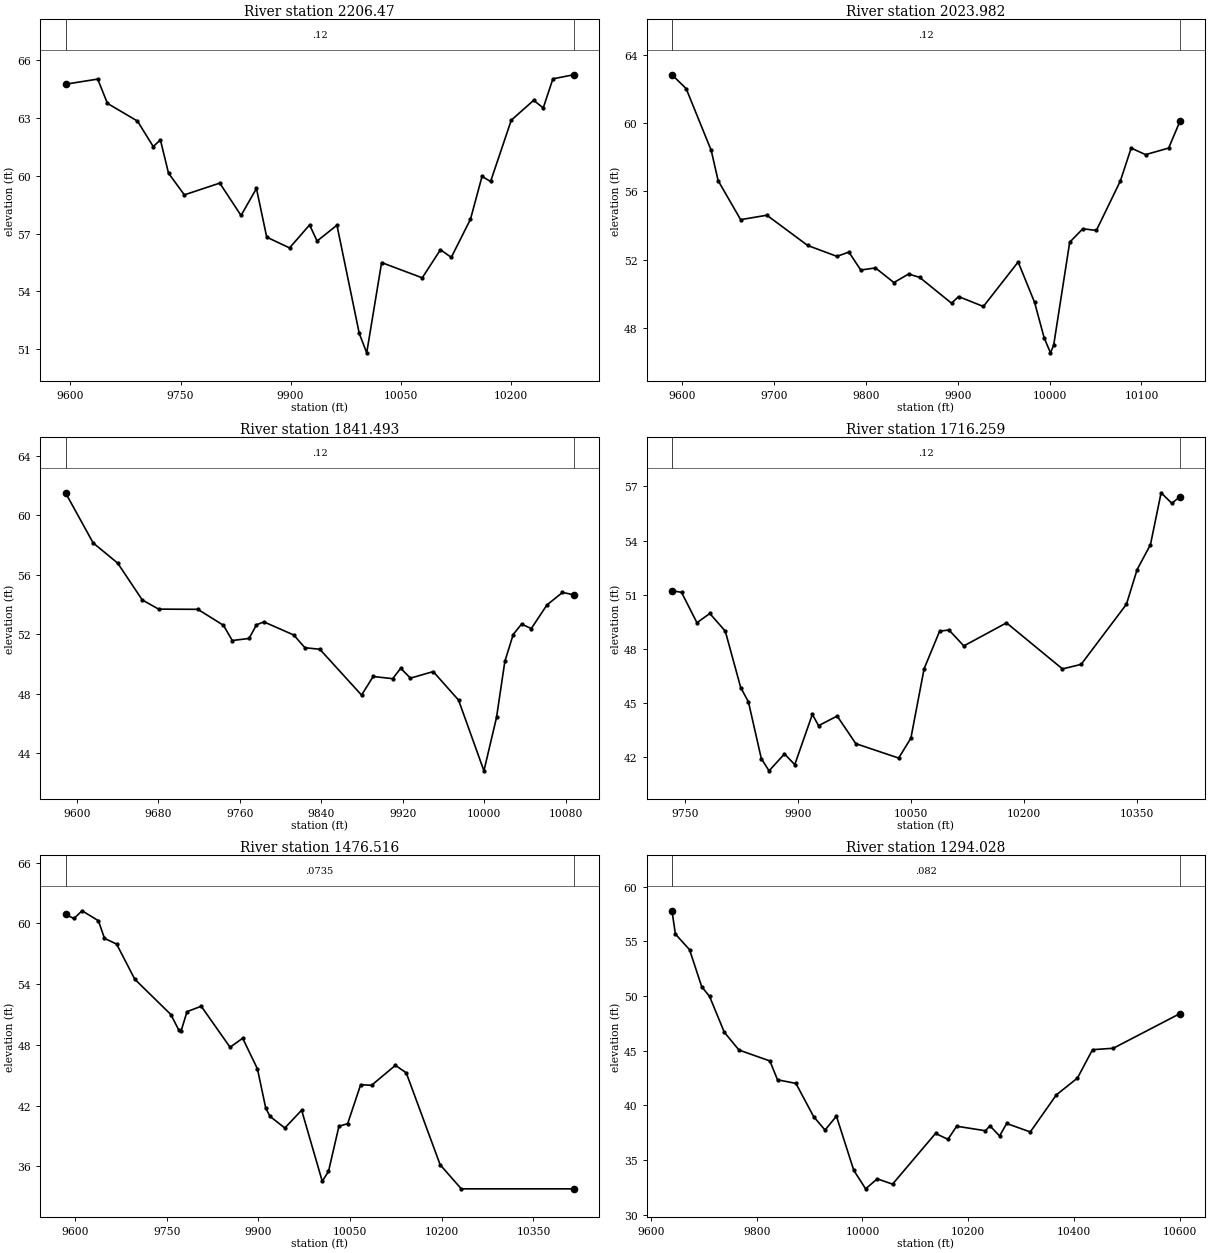
Type RM Length L Ch R = 1 , 2206.47,182.488400,182.488400,182.488400
XS GIS Cut Line= 6
1235180.40653693631071.1070245161235110.87620655630991.437002545
1235033.01658257630937.2694599981234737.48267623630839.813012312
1234657.20703448630790.0088780171234595.10374691630732.249518558
#Sta/Elev= 30
9593.20564.761399637.11165.026069650.32863.765529691.28862.845719712.77561.52167
9722.538 61.87039733.58460.14178 9755.1859.013249803.42659.624639832.43357.94229
9853.43859.346329867.441 56.8178 9898.5656.258839925.86757.452079936.08656.61662
9963.13957.437539993.57551.8154110003.7150.8086310024.0355.4977310079.3954.70433
10104.1756.16291   1011955.7677710145.12 57.747310160.8759.9714910172.5659.70823
10200.7362.8923210231.2163.92406 10244.363.5300210257.4865.0401310285.6165.25073
#Mann= 3 , 0 , 0
9593.205    0.12       09593.205    0.12       010285.61    0.12       0
#XS Ineff= 2 , 0
       09955.756                       0
Bank Sta=9593.205,10285.61
Exp/Cntr=0.3,0.1

Type RM Length L Ch R = 1 ,2023.982,182.488500,182.488500,182.488500
XS GIS Cut Line= 6
1235174.87815073 630957.428374611235113.00955155630866.728032943
1235044.72841544630800.8280185981234910.30705098630713.738539457
1234840.19463336630686.6719504971234740.86169053630635.411296657
#Sta/Elev= 30
9589.28362.817659604.71562.007889631.98658.390149639.48856.62548 9663.9754.34224
9692.53254.60107 9736.8752.832049768.745 52.19389781.70952.445689794.639 51.3945
9810.64451.518579830.64950.661839846.65451.159979858.65750.965959893.33949.45494
9901.04249.841869928.004 49.26229965.842 51.8648 9983.7349.500219994.09447.43092
10000.9946.5501310004.4846.9988410021.9153.02092 10036.253.80902 10050.953.70955
10077.0256.6063910088.7658.5286710104.4358.1461510129.5758.53051 10141.960.10869
#Mann= 3 , 0 , 0
9589.283    0.12       09589.283    0.12       0 10141.9    0.12       0
#XS Ineff= 2 , 0
       09917.088        10119.05       0
Bank Sta=9589.283,10141.9
Exp/Cntr=0.3,0.1

Type RM Length L Ch R = 1 ,1841.493,125.233800,125.233800,125.233800
XS GIS Cut Line= 6
1235196.55146208630954.6292330541235121.02555023630785.778501859
1235060.85687667630670.9028826041235040.99366219630640.614112543
1234978.14258029630558.5138191891234939.93136461630535.530068412
#Sta/Elev= 30
 9588.7661.502489615.936 58.13149640.04256.774689664.14754.301159680.21753.68561
9718.73253.672719743.89152.598249752.53451.577359769.04951.715229776.28452.63105
9783.60552.829319812.89151.948669823.87451.091419838.517 50.99019879.50547.90994
9890.88949.160149910.07949.013139917.926 49.71119927.541  49.0499949.86649.49006
9974.76247.57471 9999.6842.8215610012.0446.4055710020.2450.1793710028.4451.98062
 10036.652.68015 10046.252.3797510061.5253.9640710076.8354.8070310087.6954.65129
#Mann= 3 , 0 , 0
 9588.76    0.12       0 9588.76    0.12       010087.69    0.12       0
#XS Ineff= 2 , 0
       09939.918        10062.25       0
Bank Sta=9588.76,10087.69
Exp/Cntr=0.3,0.1

Type RM Length L Ch R = 1 ,1716.259,239.743100,239.743100,239.743100
XS GIS Cut Line= 4
1235227.93146184630792.3543146551235179.73238853630629.292757675
1235047.66026533630456.097636729 1234781.6189639630347.664771244
#Sta/Elev= 30
9732.32951.217619744.99251.129949765.51949.444879782.62549.956299803.15248.98001
9823.67945.851599833.94245.055449851.048  41.9149861.31141.235379881.83842.17177
9895.52341.579839918.86944.364559927.12143.739289951.87644.272549976.63242.74195
 10033.641.9438310049.8343.04908 10067.446.8961310088.0348.9773910100.4149.04141
10120.17 48.158810176.8649.4371310251.2646.8853110276.0647.1359610336.2950.47041
10350.46 52.389910368.1753.7698710382.34 56.647210396.5256.0660310407.4656.42744
#Mann= 3 , 0 , 0
9732.329    0.12       09732.329    0.12       010407.46    0.12       0
#XS Ineff= 2 , 0
       09949.538        10045.08       0
Bank Sta=9732.329,10407.46
Exp/Cntr=0.3,0.1

Type RM Length L Ch R = 1 ,1476.516,182.488400,182.488400,182.488400
XS GIS Cut Line= 6
1235276.24222415 631036.54138939 1235259.1592769630923.174172107
1235266.16518684 630810.019350911235325.54595485630602.634079769
1235397.60513794630413.1027615611235435.69878806630233.181308179
#Sta/Elev= 30
9584.43560.893689598.23160.486849611.59461.249849638.29760.262939648.20758.52079
9668.02657.960189697.75554.484699756.83850.990829769.99949.429779773.28949.31882
9783.23951.281229806.46351.813779853.672 47.76179874.26348.652529898.41845.62483
9912.014 41.74049919.12140.921569943.276 39.77989970.69441.5409610004.4734.51249
10014.6635.4885410031.7739.9557410045.98  40.20610067.2944.0602510085.0443.99892
10124.11 45.973310141.8645.2334210197.3436.1441510231.91 33.766410415.55 33.7664
#Mann= 3 , 0 , 0
9584.435  0.0735       09584.435  0.0735       010415.55  0.0735       0
#XS Ineff= 2 , 0
       0                10078.53       0
Bank Sta=9584.435,10415.55
Exp/Cntr=0.3,0.1

Type RM Length L Ch R = 1 ,1294.028,352.601800,352.601800,352.601800
XS GIS Cut Line= 6
 1235320.2489328631028.5442609381235399.08004607630885.444453741
1235524.51791228630620.1562241791235570.89955992630542.398566746
1235647.49269069630460.5333633221235874.33830365630261.953262791
#Sta/Elev= 30
9639.59457.800089646.07255.671659672.87454.238169695.847 50.86039710.74949.96093
9738.53846.696619766.28945.064999824.88944.060689839.27742.341069874.16842.00932
9907.61838.972079929.199 37.74189950.78139.013349983.57934.0615510006.0232.36565
10028.0233.2799810056.9932.79574 10138.337.4338510161.7236.8956410178.3238.09386
10232.6337.6796710241.2738.1270810259.4937.2025210272.8838.3441610317.6137.56973
10366.9740.9631110406.8242.4979810435.3345.0935210474.5845.22412 10600.948.39814
#Mann= 3 , 0 , 0
9639.594   0.082       09639.594   0.082       0 10600.9   0.082       0
#XS Ineff= 2 , 0
       0                               0
Bank Sta=9639.594,10600.9
Exp/Cntr=0.3,0.1

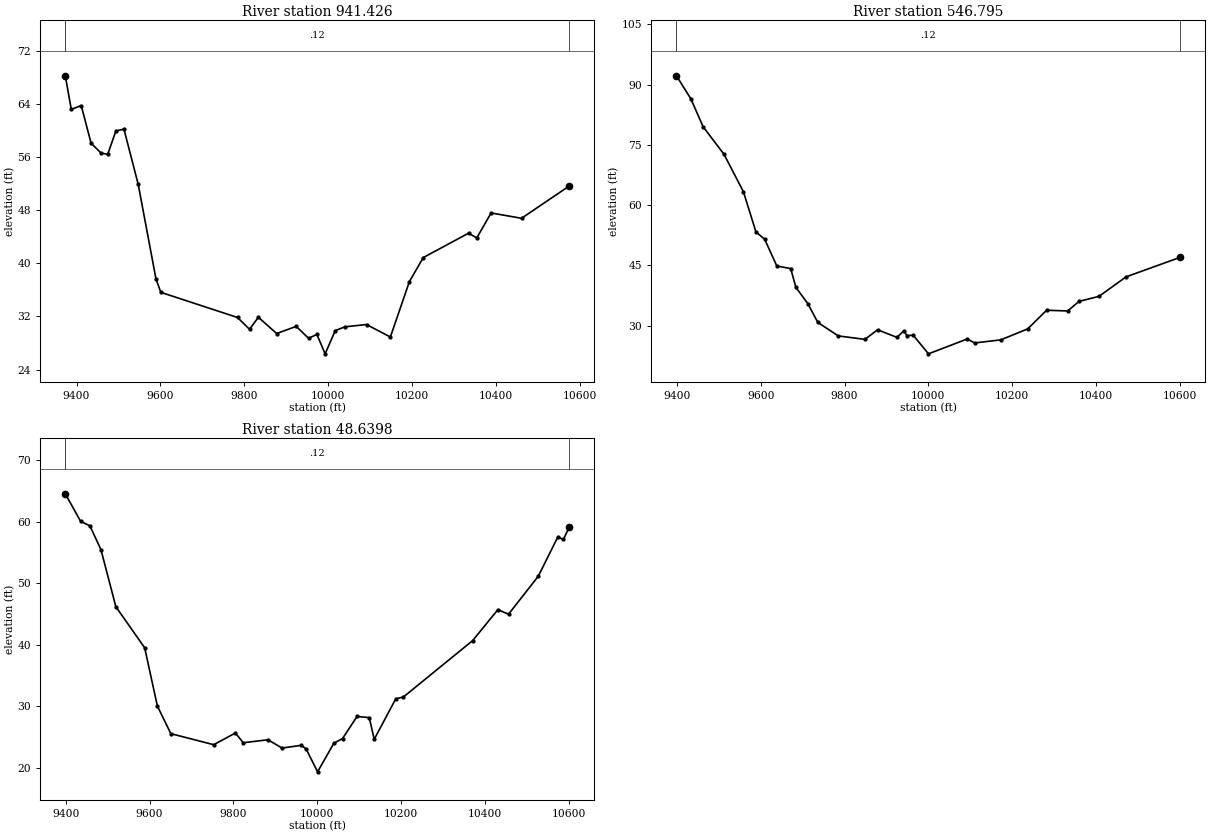
Type RM Length L Ch R = 1 , 941.426,394.631000,394.631000,394.631000
XS GIS Cut Line= 6
1235589.85171214631284.2601522911235817.97987776630885.743224242
1235824.33656206630631.9741718261235851.50244224630529.306726143
1235934.06709973630404.3663348571236091.38069025 630237.93780766
#Sta/Elev= 30
 9373.2668.231139387.58263.162029411.22463.754379434.86758.07359 9458.5156.60161
9474.27156.397279493.97359.926639513.16660.202059547.09451.916819589.71437.60934
9601.19635.628449784.07631.845029812.78830.06805 9833.8731.87607 9877.6129.42654
9924.05530.508599953.62828.709569973.37329.298839993.13826.3720710017.1829.86837
10040.1130.43559 10091.830.7878510148.7528.9037810194.0437.2342510227.2140.86497
10335.2644.5313310354.8743.8218210389.1247.58092 10461.646.7768710575.0151.62031
#Mann= 3 , 0 , 0
 9373.26    0.12       0 9373.26    0.12       010575.01    0.12       0
#XS Ineff= 2 , 0
       0                               0
Bank Sta=9373.26,10575.01
Exp/Cntr=0.3,0.1

Type RM Length L Ch R = 1 , 546.795,498.155200,498.155200,498.155200
XS GIS Cut Line= 6
1235678.40943385631485.3694172211235805.79631629631336.130692303
1235909.04340351631195.5771392441236155.52657901630736.025418958
1236237.58700714630611.5667322161236335.86263988630484.921335375
#Sta/Elev= 30
9399.03792.206339433.55586.430069462.70379.507259512.64872.631219558.81263.32664
9588.63853.337549609.52651.499189638.50644.842779671.62644.198299684.04639.50647
9712.32435.502989736.24630.809669784.98727.435139848.66926.576079878.77528.95861
9925.17227.073379941.653 28.70449949.04727.516039963.836 27.617910000.3422.97263
10092.4826.6628510110.7425.6868810172.9726.4559610237.0129.1829910282.2133.82739
10332.4133.65093 10359.636.0342910407.1437.2866910471.7542.1386510600.9547.00904
#Mann= 3 , 0 , 0
9399.037    0.12       09399.037    0.12       010600.95    0.12       0
#XS Ineff= 2 , 0
       0                               0
Bank Sta=9399.037,10600.95
Exp/Cntr=0.3,0.1

Type RM Length L Ch R = 1 , 48.6398,0.000000,0.000000,0.000000
XS GIS Cut Line= 6
1235899.56633827631487.0111056781236073.97923101631334.131993449
1236173.31653467631255.5177009371236327.39589121631167.287659206
1236438.12063947631068.1389728541236874.73954385630792.512606309
#Sta/Elev= 30
9399.11364.524359435.80360.026199457.80359.319549484.203 55.43869519.70146.16555
9588.499 39.48249618.82430.003039650.96325.519429753.23723.72613 9805.0525.63285
 9823.5924.044139882.652 24.52799916.19523.181089961.638 23.62139973.48523.06298
   1000119.3140910039.8123.9701510060.4824.7229310095.1628.3204710124.3328.13315
10136.0524.6005810187.5331.19859 10205.4 31.464210370.9740.6580310431.1445.69312
10456.4344.9393910527.2951.0989610573.9157.4746910587.3857.0991810600.9159.04519
#Mann= 3 , 0 , 0
9399.113    0.12       09399.113    0.12       010600.91    0.12       0
#XS Ineff= 2 , 0
       0                               0
Bank Sta=9399.113,10600.91
Exp/Cntr=0.3,0.1